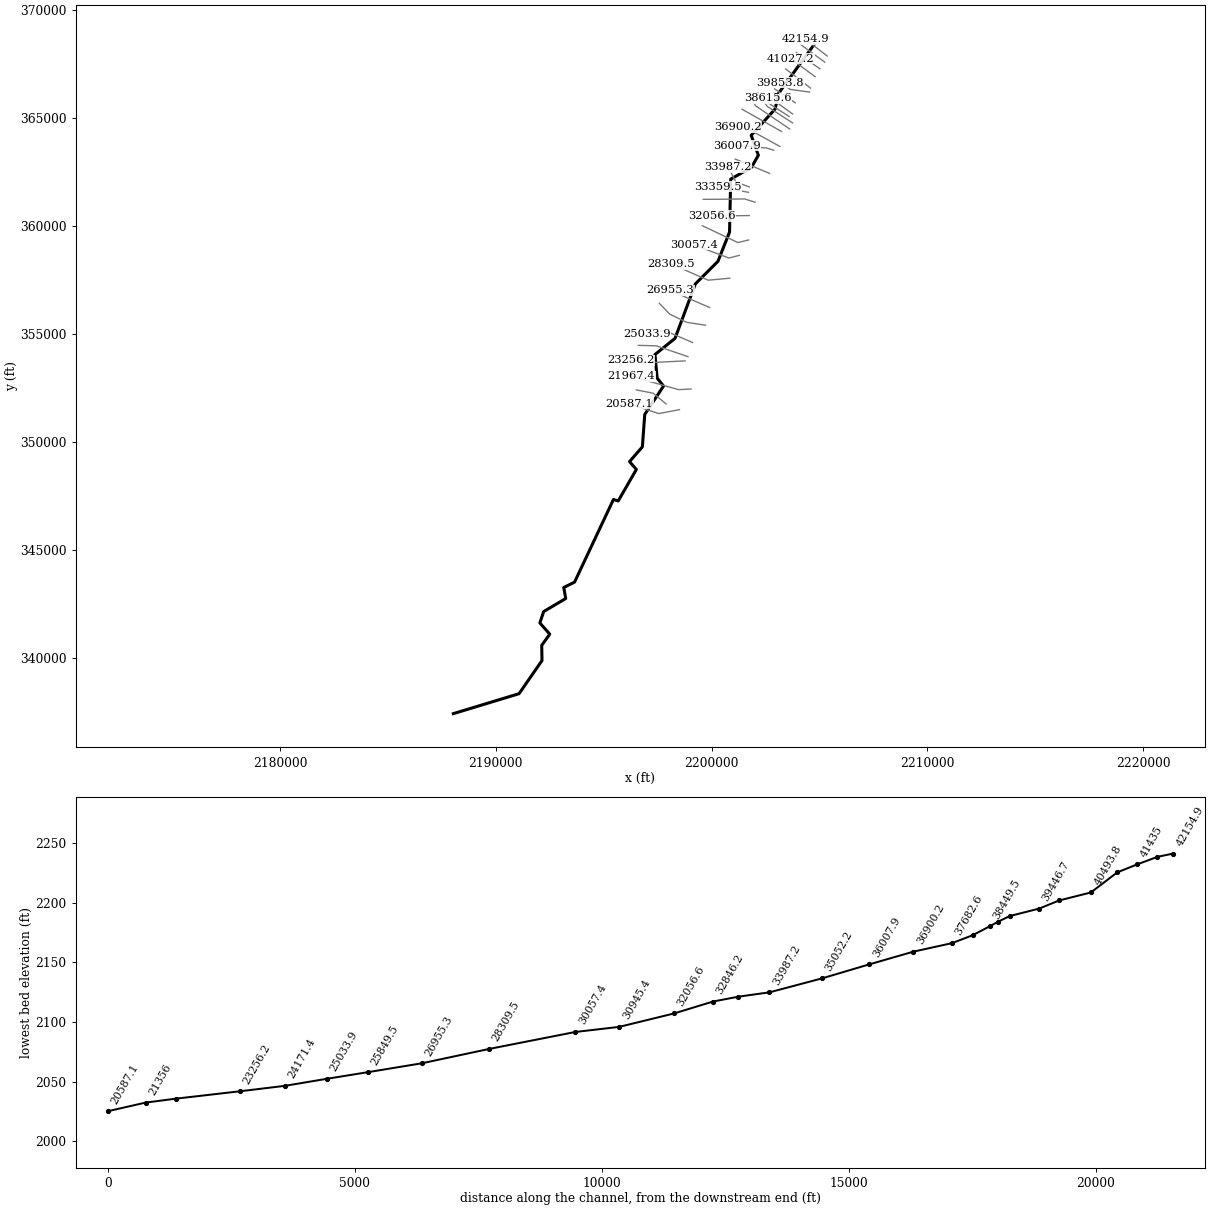
--- LittleCk.prj (project) ---

Proj Title=LittleCk
Current Plan=p01
Default Exp/Contr=0,0
English Units
Geom File=g01
Flow File=f01
Plan File=p01
BEGIN DESCRIPTION:
END DESCRIPTION:
DSS Export Rating Curves= 0
DSS Export Rating Curve Sorted= 0
DSS Export Volume Flow Curves= 0
DXF OffsetX= 0
DXF OffsetY= 0
DXF ScaleX= 0
DXF ScaleY= 0

--- LittleCk.p01 (plan) ---

Plan Title=Floodplain
Program Version=4.00
Geom File=g01
Flow File=f01
K Sum by GR=0
Std Step Tol=0.01
Critical Tol=0.01
Num of Std Step Trials=20
Max Error Tol=0.3
Flow Tol Ratio=0.001
Split Flow NTrial=30
Split Flow Tol=0.02
Split Flow Ratio=0.02
Log Output Level=0
Friction Slope Method=1
Unsteady Friction Slope Method=2
Unsteady Bridges Friction Slope Method=1
Global Log Level=0
CheckData=False
Run HTab=0
Run UNet=0
Run PostProcess=0
UNET Theta=0
UNET Theta Warmup=0
UNET ZTol=0
UNET ZSATol=0
UNET MxIter=0
UNET MaxInSteps=0
UNET DtIC=0
UNET DtMin=0
UNET MaxCRTS=0
UNET WFStab=0
UNET SFStab=0
UNET WFX=0
UNET SFX=0
UNET DSS MLevel=0
UNET DZMax Abort=0
UNET Convert EG Bridges=0
UNET Use Existing IB Tables=0
UNET Froude Limit=0
UNET Froude Power=0
Write IC File=0
Echo Input=False
Echo Output=False
Write Detailed=0

--- LittleCk.f01 (steady flow) ---

Flow Title=NFF Regression Equation
Program Version=4.00
Number of Profiles=1
Profile Names=P100yr
River Rch & RM=LittleCk,Main      ,42154.9
535.6406
River Rch & RM=LittleCk,Main      ,41027.2
594.3168
River Rch & RM=LittleCk,Main      ,39853.8
604.2845
River Rch & RM=LittleCk,Main      ,39446.7
720.9590
River Rch & RM=LittleCk,Main      ,38098
732.3577
River Rch & RM=LittleCk,Main      ,37682.6
896.7325
River Rch & RM=LittleCk,Main      ,36900.2
921.8796
River Rch & RM=LittleCk,Main      ,36007.9
1015.591
River Rch & RM=LittleCk,Main      ,35052.2
1052.120
River Rch & RM=LittleCk,Main      ,32846.2
1164.951
River Rch & RM=LittleCk,Main      ,28309.5
1256.919
River Rch & RM=LittleCk,Main      ,24171.4
1381.316
River Rch & RM=LittleCk,Main      ,23256.2
1578.539
River Rch & RM=LittleCk,Main      ,21967.4
1662.490
River Rch & RM=LittleCk,Main      ,19445.3
1777.367
River Rch & RM=LittleCk,Main      ,16166.9
1973.731
River Rch & RM=LittleCk,Main      ,13337.2
2130.546
River Rch & RM=LittleCk,Main      ,9150.5
2364.077
River Rch & RM=LittleCk,Main      ,146.9
2598.877
Boundary for River Rch & Prof#=LittleCk,Main      ,1
Up Type=0
Dn Type=3
Dn Slope=0.003318

--- LittleCk.g01 (geometry) ---

Geom Title=USGS 10m DEM
Program Version=4.00

River Reach=LittleCk     ,Main
Reach XY= 30
     2204747.108      368371.258     2203109.778      366127.332
     2202947.617      365397.192     2201839.178      364180.214
     2202170.465      363259.158     2201850.313      362695.035
     2200888.854      362153.892     2200834.528      359702.517
     2200297.560      358347.826     2199250.153      357303.689
     2198307.965      354784.158     2197377.295      354032.344
     2197480.621      352938.455     2197774.762      352575.173
     2196904.059      351259.158     2196793.860      349760.059
     2196198.590      349078.298     2196514.996      348715.017
     2195673.590      347254.861     2195453.278      347324.002
     2193650.934      343500.173     2193149.371      343249.392
     2193240.777      342739.627     2192218.339      342137.813
     2192041.949      341611.111     2192500.153      341091.970
     2192128.668      340574.001     2192140.387      339869.705
     2191078.668      338335.720     2188030.075      337411.485

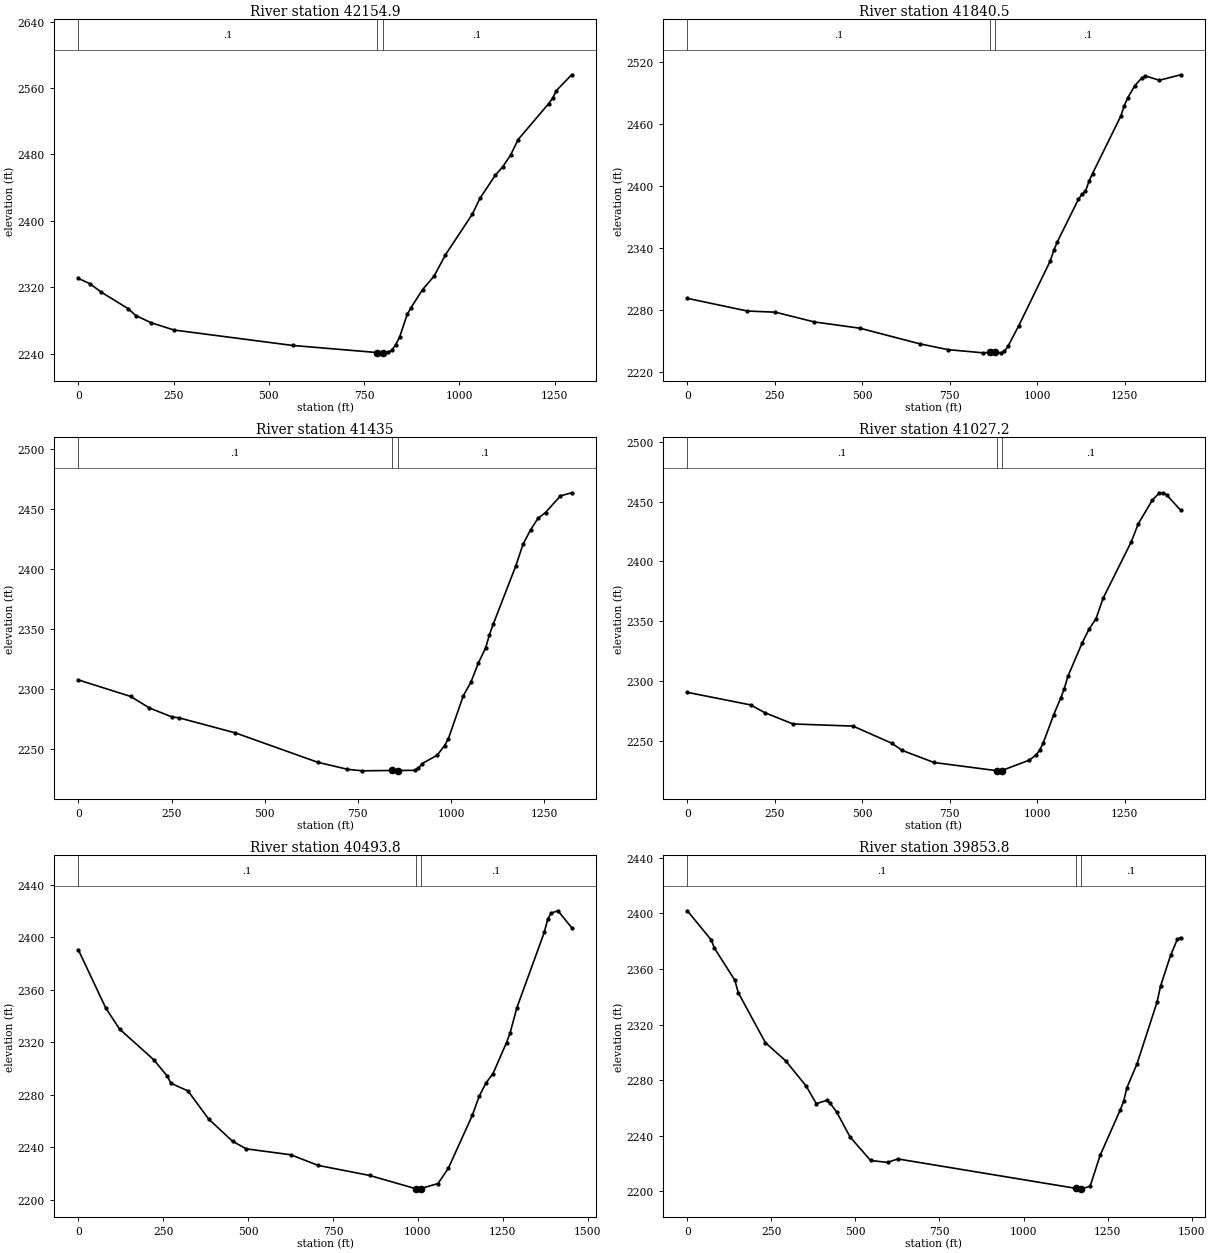
Type RM Length L Ch R = 1 ,42154.9,313.9,314.5,315
XS GIS Cut Line= 2
     2205364.913      367850.530     2204336.646      368637.130
#Sta/Elev= 30
       0 2330.68    30.1 2324.35    60.2 2314.13   130.5 2294.26   150.5 2286.01
   190.7 2277.36   250.9 2268.53   562.0 2249.96   783.4 2241.43   798.4 2241.11
   802.9 2241.05   812.9 2241.55   822.9 2244.53   833.0 2251.03   843.0 2260.07
   863.1 2287.62   873.1 2295.59   903.2 2317.24   933.3 2333.30   963.4 2359.15
  1033.7 2407.98  1053.8 2427.12  1093.9 2454.84  1114.0 2465.41  1134.1 2479.10
  1154.1 2497.99  1234.4 2541.37  1244.4 2547.70  1254.5 2557.01  1294.6 2576.01
#Mann= 3 , 0 , 0
       0     0.1       0   783.4   0.045       0   798.4     0.1       0
Bank Sta=   783.4,   798.4
Exp/Cntr=0.3,0.1

Type RM Length L Ch R = 1 ,41840.5,404.8,405.4,406
XS GIS Cut Line= 2
     2205248.397      367569.649     2204108.862      368400.634
#Sta/Elev= 30
       0 2291.18   171.3 2278.89   251.8 2277.73   362.7 2268.33   493.6 2262.20
   664.9 2247.06   745.5 2241.42   846.2 2238.34     864 2238.71     879 2238.87
   896.6 2238.43   906.6 2239.87   916.7 2244.65   947.0 2264.20  1037.6 2327.35
  1047.7 2337.62  1057.8 2345.83  1118.2 2387.23  1128.3 2392.01  1138.4 2394.97
  1148.4 2404.59  1158.5 2412.12  1239.1 2467.59  1249.2 2477.87  1259.2 2485.56
  1279.4 2497.24  1299.5 2504.87  1309.6 2506.75  1349.9 2502.56  1410.4 2507.87
#Mann= 3 , 0 , 0
       0     0.1       0     864   0.045       0     879     0.1       0
Bank Sta=     864,     879
Exp/Cntr=0.3,0.1

Type RM Length L Ch R = 1 ,41435,408.3,407.7,407.1
XS GIS Cut Line= 2
     2205026.674      367259.646     2203936.533      368011.043
#Sta/Elev= 30
       0 2307.78   140.4 2294.01   190.6 2284.44   250.8 2277.01   270.8 2276.16
   421.3 2263.69   641.9 2239.28   722.2 2233.37   762.3 2232.09   841.8 2232.41
   856.8 2232.37   902.7 2232.52   912.8 2234.20   922.8 2238.14   962.9 2245.09
   983.0 2253.17   993.0 2258.78  1033.1 2294.59  1053.2 2305.67  1073.2 2321.59
  1093.3 2334.67  1103.3 2345.47  1113.4 2354.16  1173.6 2402.37  1193.6 2420.88
  1213.7 2432.76  1233.7 2442.38  1253.8 2447.16  1293.9 2461.05  1324.0 2463.60
#Mann= 3 , 0 , 0
       0     0.1       0   841.8   0.045       0   856.8     0.1       0
Bank Sta=   841.8,   856.8
Exp/Cntr=0.3,0.1

Type RM Length L Ch R = 1 ,41027.2,534.4,533.4,532.3
XS GIS Cut Line= 2
     2204801.024      366898.080     2203663.771      367732.066
#Sta/Elev= 30
       0 2290.83   181.3 2280.31   221.6 2273.83   302.2 2264.44   473.4 2262.67
   584.3 2248.41   614.5 2242.35   705.1 2232.30     884 2225.48   886.5 2225.33
     899 2225.57   977.1 2234.18   997.3 2238.55  1007.3 2242.60  1017.4 2248.49
  1047.6 2272.26  1067.8 2286.22  1077.8 2293.96  1087.9 2304.07  1128.2 2331.66
  1148.4 2343.46  1168.5 2352.33  1188.7 2369.31  1269.2 2416.41  1289.4 2431.60
  1329.7 2451.27  1349.8 2457.32  1359.9 2457.21  1370.0 2455.65  1410.3 2442.77
#Mann= 3 , 0 , 0
       0     0.1       0     884   0.045       0     899     0.1       0
Bank Sta=     884,     899
Exp/Cntr=0.3,0.1

Type RM Length L Ch R = 1 ,40493.8,638.5,640.1,641.7
XS GIS Cut Line= 2
     2204587.789      366367.361     2203436.320      367253.471
#Sta/Elev= 30
       0 2390.43    80.7 2346.18   121.1 2330.22   222.0 2306.80   262.3 2294.15
   272.4 2288.93   322.9 2283.03   383.4 2261.71   454.0 2244.72   494.4 2238.95
   625.6 2234.42   706.3 2226.33   857.6 2218.69   993.9 2208.57   998.9 2208.48
  1008.9 2208.71  1059.4 2212.54  1089.7 2224.16  1160.3 2264.44  1180.5 2278.96
  1200.7 2289.23  1220.9 2296.06  1261.2 2319.92  1271.3 2326.98  1291.5 2346.35
  1372.2 2403.76  1382.3 2413.67  1392.4 2418.52  1412.6 2420.26  1453.0 2407.40
#Mann= 3 , 0 , 0
       0     0.1       0   993.9   0.045       0  1008.9     0.1       0
Bank Sta=   993.9,  1008.9
Exp/Cntr=0.3,0.1

Type RM Length L Ch R = 1 ,39853.8,407.8,407,406.1
XS GIS Cut Line= 3
     2204549.881      366182.557     2203649.555      366305.760
     2203189.915      366623.243
#Sta/Elev= 30
       0 2401.82    70.7 2380.99    80.8 2374.90   141.4 2351.82   151.4 2342.96
   232.2 2306.97   292.8 2293.81   353.4 2275.78   383.7 2263.09   414.0 2265.39
   424.1 2263.66   444.3 2257.03   484.6 2238.95   545.2 2222.21   595.7 2220.82
   626.0 2223.33  1157.1 2202.12  1168.1 2201.82  1172.1 2201.85  1198.0 2203.62
  1227.9 2225.90  1287.8 2258.63  1297.8 2264.76  1307.7 2274.69  1337.7 2291.75
  1397.5 2336.40  1407.5 2347.57  1437.4 2369.68  1457.4 2381.22  1467.3 2382.53
#Mann= 3 , 0 , 0
       0     0.1       0  1157.1   0.045       0  1172.1     0.1       0
Bank Sta=  1157.1,  1172.1
Exp/Cntr=0.3,0.1

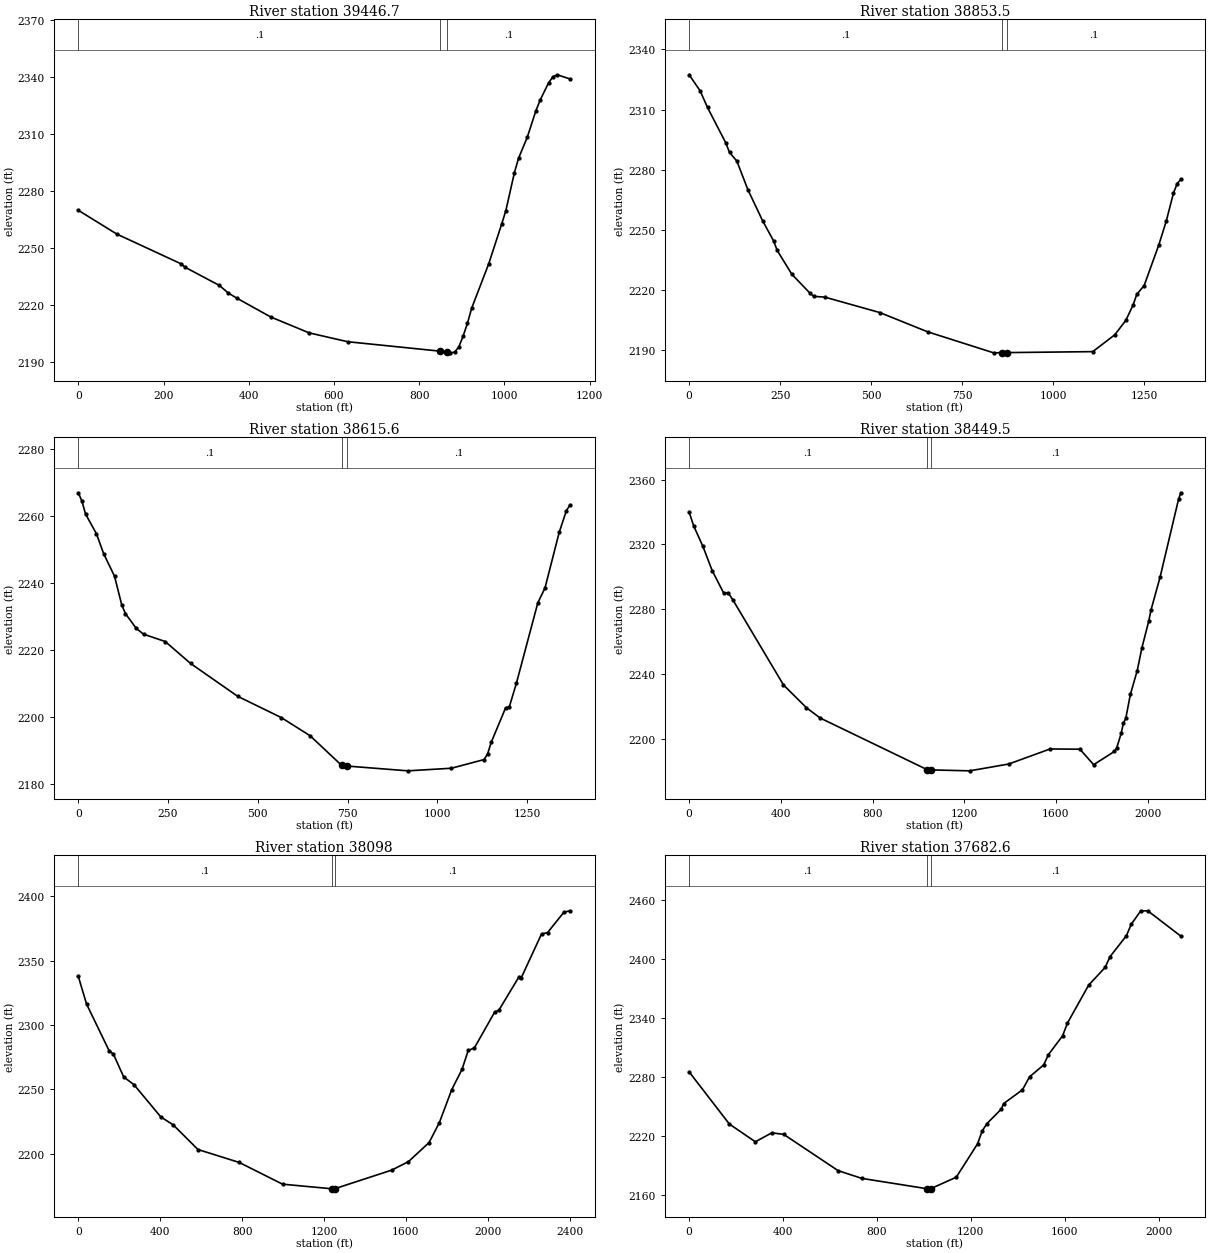
Type RM Length L Ch R = 1 ,39446.7,591.8,592.7,593.2
XS GIS Cut Line= 2
     2203881.744      365685.009     2202924.556      366329.453
#Sta/Elev= 30
       0 2269.92    90.3 2257.43   240.8 2241.81   250.8 2239.95   331.1 2230.40
   351.2 2226.55   371.3 2223.81   451.5 2213.83   541.8 2205.46   632.1 2200.82
   849.7 2195.84   864.7 2195.27   873.0 2194.97   883.0 2195.32   893.0 2198.10
   903.1 2203.78   913.1 2210.43   923.1 2218.39   963.3 2241.88   993.4 2262.56
  1003.4 2269.78  1023.5 2289.78  1033.5 2297.49  1053.6 2308.30  1073.6 2322.07
  1083.7 2327.81  1103.7 2336.95  1113.8 2340.12  1123.8 2341.18  1153.9 2338.99
#Mann= 3 , 0 , 0
       0     0.1       0   849.7   0.045       0   864.7     0.1       0
Bank Sta=   849.7,   864.7
Exp/Cntr=0.3,0.1

Type RM Length L Ch R = 1 ,38853.5,236.2,237.7,239.2
XS GIS Cut Line= 2
     2203758.542      365168.506     2202663.935      365959.845
#Sta/Elev= 30
       0 2327.32    30.2 2319.32    50.4 2311.02   100.8 2293.32   110.9 2288.60
   131.0 2284.34   161.3 2270.06   201.6 2254.64   231.8 2244.59   241.9 2239.78
   282.2 2227.87   332.6 2218.36   342.7 2216.90   373.0 2216.50   524.2 2208.80
   655.2 2199.22   836.6 2188.75   858.8 2188.84   873.8 2188.87  1108.8 2189.35
  1169.3 2197.75  1199.5 2204.90  1219.7 2212.63  1229.7 2217.93  1249.9 2222.26
  1290.2 2242.53  1310.4 2254.24  1330.5 2268.37  1340.6 2273.06  1350.7 2275.20
#Mann= 3 , 0 , 0
       0     0.1       0   858.8   0.045       0   873.8     0.1       0
Bank Sta=   858.8,   873.8
Exp/Cntr=0.3,0.1

Type RM Length L Ch R = 1 ,38615.6,164.1,166.1,168.2
XS GIS Cut Line= 3
     2203597.626      365051.798     2202614.981      365687.962
     2202603.621      365886.763
#Sta/Elev= 30
       0 2267.01    10.1 2264.50    20.2 2260.65    50.5 2254.78    70.6 2248.82
   100.9 2242.09   121.1 2233.50   131.2 2230.94   161.5 2226.52   181.6 2224.80
   242.2 2222.60   312.8 2216.05   444.0 2206.25   565.1 2199.92   645.8 2194.47
   733.6 2185.63   748.6 2185.43   918.3 2184.00  1039.4 2184.78  1130.2 2187.36
  1140.3 2189.10  1150.4 2192.55  1190.5 2202.85  1200.5 2203.05  1220.4 2210.14
  1280.1 2234.17  1300.0 2238.56  1339.8 2255.26  1359.8 2261.71  1369.7 2263.36
#Mann= 3 , 0 , 0
       0     0.1       0   733.6   0.045       0   748.6     0.1       0
Bank Sta=   733.6,   748.6
Exp/Cntr=0.3,0.1

Type RM Length L Ch R = 1 ,38449.5,352.7,351.3,349.8
XS GIS Cut Line= 3
     2203753.803      364756.252     2202584.952      365516.834
     2202160.768      366136.028
#Sta/Elev= 30
       0 2339.93    20.1 2331.33    60.2 2318.75   100.3 2303.90   150.5 2290.03
   170.6 2290.04   190.6 2285.81   411.3 2233.30   511.7 2219.17   571.9 2212.80
    1039 2180.91    1054 2180.79  1224.0 2180.21  1394.5 2184.43  1574.7 2193.72
  1704.8 2193.57  1764.8 2184.00  1854.9 2192.16  1864.9 2194.17  1884.9 2203.37
  1894.9 2209.88  1904.9 2212.59  1924.9 2227.36  1954.9 2242.13  1975.0 2256.00
  2005.0 2272.64  2015.0 2279.54  2055.0 2300.06  2135.1 2347.90  2145.1 2351.91
#Mann= 3 , 0 , 0
       0     0.1       0    1039   0.045       0    1054     0.1       0
Bank Sta=    1039,    1054
Exp/Cntr=0.3,0.1

Type RM Length L Ch R = 1 ,38098,413.9,415.4,417
XS GIS Cut Line= 3
     2203625.862      364471.938     2202042.083      365547.663
     2201815.733      365978.800
#Sta/Elev= 30
       0 2337.60    40.3 2316.15   151.2 2279.68   171.3 2277.33   221.7 2259.53
   272.1 2253.50   403.1 2228.46   463.5 2222.29   584.4 2203.16   786.0 2193.10
   997.6 2176.22  1238.3 2172.65  1249.5 2172.60  1253.3 2172.73  1531.6 2187.20
  1612.3 2193.73  1713.0 2208.50  1763.4 2224.02  1823.9 2249.66  1874.2 2265.44
  1904.5 2280.14  1934.4 2282.03  2033.8 2310.00  2053.7 2311.31  2153.1 2337.50
  2163.0 2336.41  2262.4 2370.59  2292.2 2371.73  2371.7 2387.53  2401.5 2388.64
#Mann= 3 , 0 , 0
       0     0.1       0  1238.3   0.045       0  1253.3     0.1       0
Bank Sta=  1238.3,  1253.3
Exp/Cntr=0.3,0.1

Type RM Length L Ch R = 1 ,37682.6,780.7,782.3,770.9
XS GIS Cut Line= 2
     2203243.734      364360.810     2201417.694      365386.480
#Sta/Elev= 30
       0 2285.07   171.2 2232.00   281.9 2213.93   352.4 2223.05   402.8 2221.46
   634.4 2184.56   735.0 2176.69  1014.7 2166.08  1017.0 2166.02  1029.7 2166.27
  1137.8 2177.86  1228.4 2211.82  1248.6 2225.05  1268.7 2232.52  1329.1 2247.08
  1339.2 2252.76  1419.8 2266.82  1450.0 2280.06  1510.4 2292.22  1530.5 2302.70
  1590.9 2321.84  1611.1 2334.62  1701.7 2373.39  1772.2 2391.48  1792.3 2402.19
  1862.8 2423.78  1882.9 2435.26  1923.2 2448.90  1953.4 2449.09  2094.4 2423.26
#Mann= 3 , 0 , 0
       0     0.1       0  1014.7   0.045       0  1029.7     0.1       0
Bank Sta=  1014.7,  1029.7
Exp/Cntr=0.3,0.1

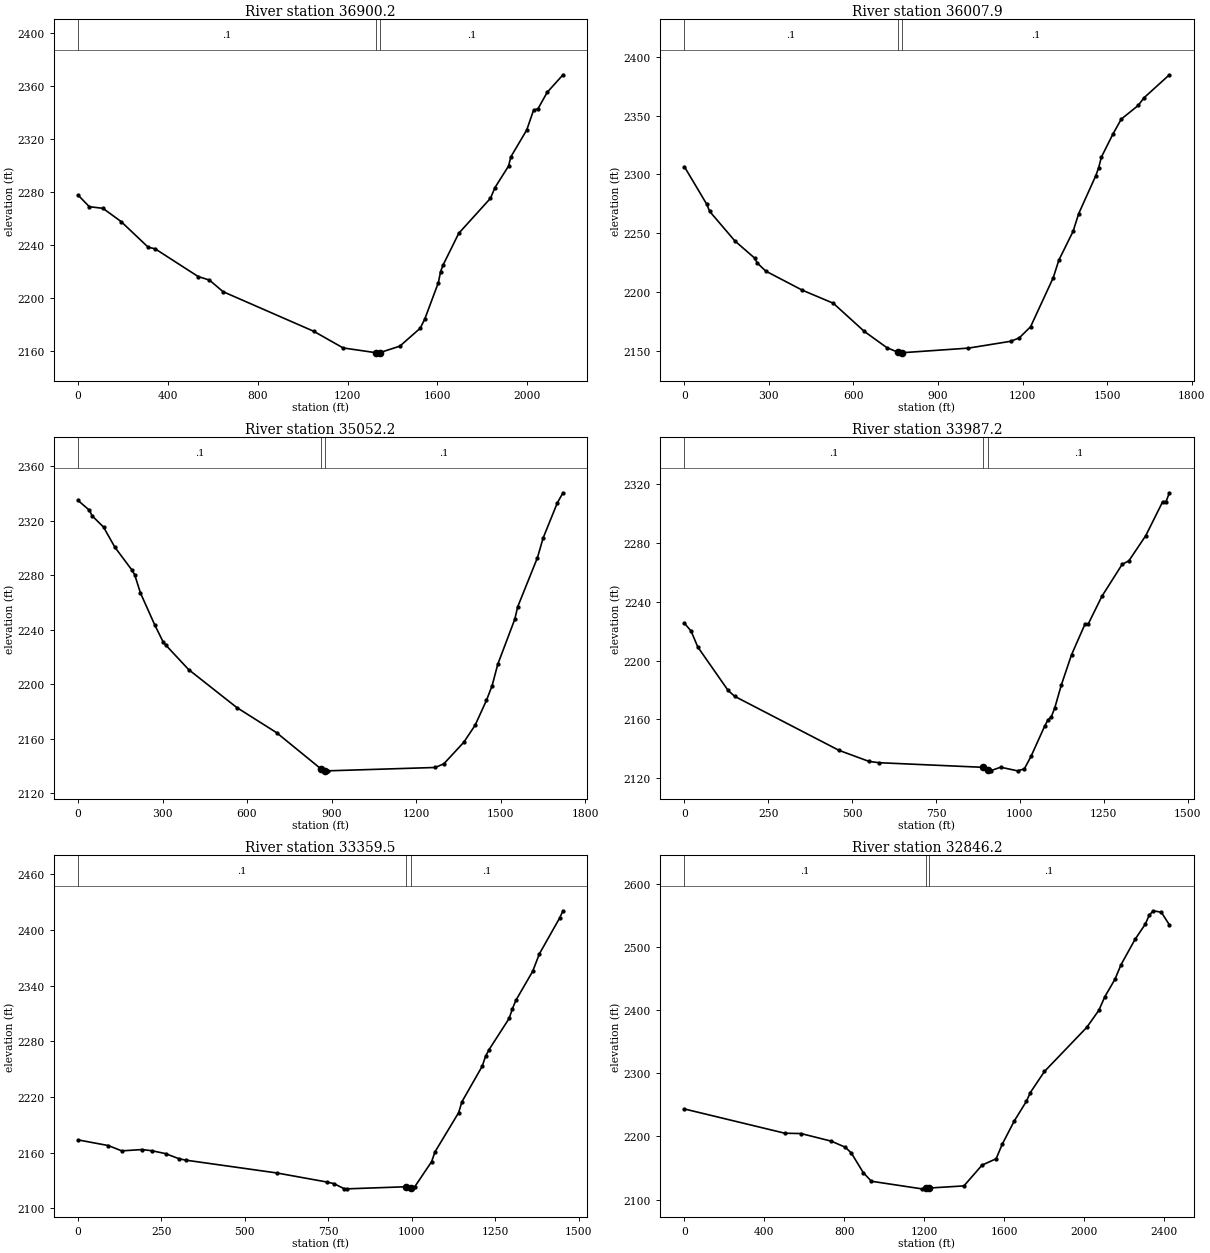
Type RM Length L Ch R = 1 ,36900.2,885.3,892,900.1
XS GIS Cut Line= 3
     2203166.222      363667.094     2201831.963      364402.512
     2201214.477      364553.005
#Sta/Elev= 30
       0 2277.73    50.4 2268.93   111.0 2267.69   191.7 2257.77   312.8 2238.36
   343.0 2237.26   534.7 2216.36   585.2 2213.66   645.7 2204.94  1049.3 2175.12
  1180.5 2162.57  1328.8 2158.92  1331.8 2158.88  1343.8 2159.04  1432.7 2163.90
  1523.5 2177.40  1543.7 2184.28  1604.2 2211.69  1614.3 2220.10  1624.4 2224.69
  1695.0 2248.88  1836.2 2275.25  1856.4 2283.36  1917.0 2299.59  1927.0 2306.46
  1997.7 2326.68  2027.9 2341.51  2048.1 2342.75  2088.4 2354.96  2159.1 2368.25
#Mann= 3 , 0 , 0
       0     0.1       0  1328.8   0.045       0  1343.8     0.1       0
Bank Sta=  1328.8,  1343.8
Exp/Cntr=0.3,0.1

Type RM Length L Ch R = 1 ,36007.9,962.7,955.8,948.9
XS GIS Cut Line= 4
     2202878.173      363491.029     2202565.398      363591.734
     2201739.228      363665.063     2201177.281      363699.214
#Sta/Elev= 30
       0 2306.56    79.7 2274.46    89.6 2268.55   179.2 2243.40   248.9 2228.89
   258.9 2224.57   288.8 2217.74   418.5 2201.51   528.4 2190.41   638.4 2166.46
   718.3 2152.68   756.2 2148.89   768.3 2148.23   771.2 2148.30  1008.1 2152.25
  1158.0 2158.07  1188.2 2160.94  1228.4 2170.41  1308.8 2212.11  1328.9 2227.18
  1379.2 2251.53  1399.3 2266.72  1459.6 2298.78  1469.7 2305.43  1479.7 2314.72
  1519.9 2333.96  1550.1 2346.98  1610.4 2358.66  1630.5 2365.06  1721.0 2384.72
#Mann= 3 , 0 , 0
       0     0.1       0   756.2   0.045       0   771.2     0.1       0
Bank Sta=   756.2,   771.2
Exp/Cntr=0.3,0.1

Type RM Length L Ch R = 1 ,35052.2,1080.9,1065.1,1049.5
XS GIS Cut Line= 2
     2202689.090      362419.559     2201099.592      363080.507
#Sta/Elev= 30
       0 2334.89    40.3 2327.68    50.3 2323.55    90.6 2315.34   130.9 2300.55
   191.3 2283.83   201.3 2280.36   221.5 2267.10   271.8 2243.84   302.0 2231.18
   312.1 2228.66   392.6 2210.81   563.8 2182.91   704.7 2164.53   862.7 2137.88
   877.7 2136.57   885.9 2136.50  1268.4 2138.97  1298.6 2141.69  1369.1 2157.42
  1409.4 2169.91  1449.6 2188.12  1469.8 2198.97  1489.9 2214.68  1550.3 2247.71
  1560.4 2256.72  1630.8 2292.92  1651.0 2307.36  1701.3 2333.06  1721.4 2340.48
#Mann= 3 , 0 , 0
       0     0.1       0   862.7   0.045       0   877.7     0.1       0
Bank Sta=   862.7,   877.7
Exp/Cntr=0.3,0.1

Type RM Length L Ch R = 1 ,33987.2,607.5,627.5,647.3
XS GIS Cut Line= 3
     2201749.660      361793.417     2201137.584      362015.444
     2200765.538      362717.531
#Sta/Elev= 30
       0 2225.45    20.0 2220.06    40.1 2209.16   130.2 2179.62   150.2 2175.55
   460.8 2138.76   550.9 2131.17   581.0 2130.33   890.7 2127.18   905.7 2125.38
   912.6 2124.86   942.8 2127.25   993.1 2124.79  1013.2 2126.10  1033.3 2134.69
  1073.5 2155.07  1083.6 2159.48  1093.6 2161.63  1103.7 2167.48  1123.8 2183.48
  1154.0 2203.94  1194.2 2224.86  1204.3 2225.15  1244.5 2243.77  1304.9 2265.56
  1325.0 2267.99  1375.3 2285.15  1425.6 2308.23  1435.6 2308.31  1445.7 2314.35
#Mann= 3 , 0 , 0
       0     0.1       0   890.7   0.045       0   905.7     0.1       0
Bank Sta=   890.7,   905.7
Exp/Cntr=0.3,0.1

Type RM Length L Ch R = 1 ,33359.5,508.8,513.3,517.8
XS GIS Cut Line= 2
     2201713.655      361541.386     2200285.479      361811.419
#Sta/Elev= 30
       0 2173.93    90.8 2167.81   131.2 2162.07   191.8 2163.50   222.1 2162.18
   262.4 2159.11   302.8 2153.60   323.0 2152.08   595.5 2138.29   746.9 2128.43
   767.1 2126.73   797.4 2121.38   807.5 2121.15   984.4 2123.42   999.4 2121.96
  1009.4 2123.48  1059.8 2150.48  1069.9 2161.01  1140.6 2203.17  1150.7 2215.05
  1211.2 2253.18  1221.3 2263.84  1231.4 2270.93  1292.0 2304.78  1302.1 2315.44
  1312.2 2324.31  1362.6 2355.57  1382.8 2374.50  1443.4 2413.06  1453.5 2420.88
#Mann= 3 , 0 , 0
       0     0.1       0   984.4   0.045       0   999.4     0.1       0
Bank Sta=   984.4,   999.4
Exp/Cntr=0.3,0.1

Type RM Length L Ch R = 1 ,32846.2,789.5,789.5,789.4
XS GIS Cut Line= 4
     2202020.997      361083.372     2201541.761      361235.572
     2200334.282      361220.906     2199618.444      361217.778
#Sta/Elev= 30
       0 2243.56   502.8 2205.12   583.3 2204.64   734.3 2192.62   804.7 2183.02
   834.9 2173.94   895.3 2142.55   935.5 2129.10  1187.1 2117.10  1209.1 2117.80
  1224.1 2118.36  1398.4 2121.76  1489.0 2154.64  1559.4 2164.71  1589.6 2187.50
  1650.0 2224.42  1710.4 2255.45  1730.6 2269.54  1801.1 2302.87  2012.9 2372.76
  2073.4 2399.80  2103.6 2421.47  2154.0 2448.96  2184.3 2472.03  2254.8 2512.26
  2305.2 2535.92  2325.4 2550.41  2345.6 2557.30  2385.9 2554.94  2426.2 2535.02
#Mann= 3 , 0 , 0
       0     0.1       0  1209.1   0.045       0  1224.1     0.1       0
Bank Sta=  1209.1,  1224.1
Exp/Cntr=0.3,0.1

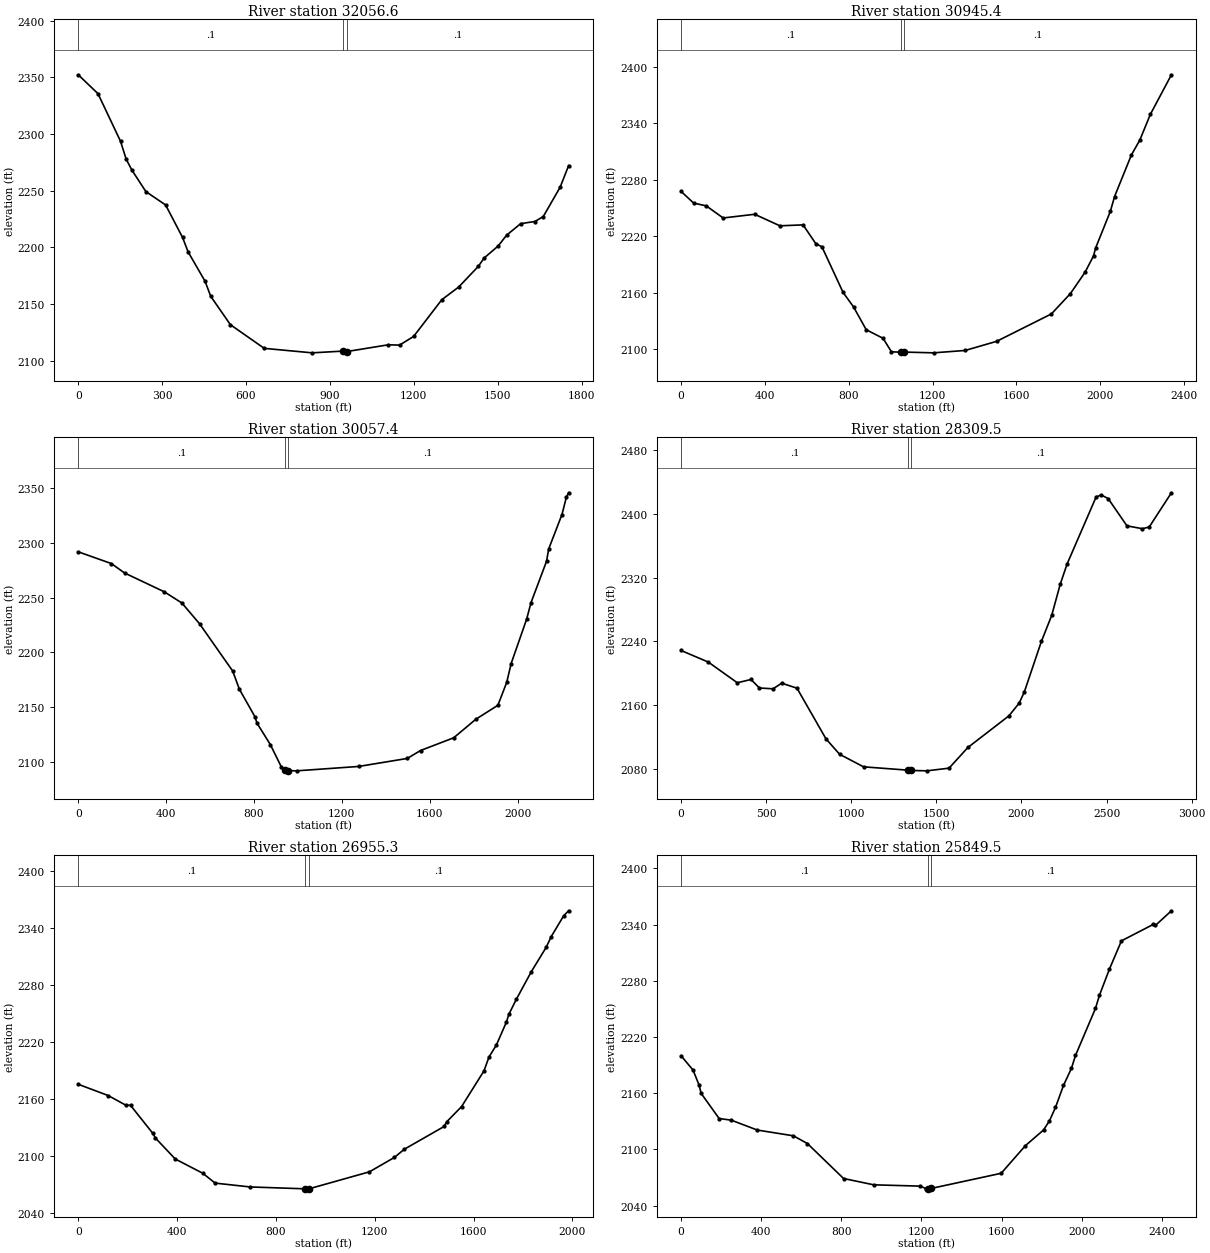
Type RM Length L Ch R = 1 ,32056.6,1120.7,1110.8,1100.9
XS GIS Cut Line= 2
     2201749.268      360467.432     2199995.505      360443.732
#Sta/Elev= 30
       0 2352.33    70.6 2335.67   151.2 2293.69   171.4 2277.92   191.5 2268.39
   241.9 2249.32   312.5 2237.49   373.0 2208.92   393.1 2196.05   453.6 2170.22
   473.8 2156.95   544.3 2131.89   665.3 2111.04   836.6 2107.09   946.6 2108.61
   961.6 2108.27  1108.8 2114.18  1149.1 2113.90  1199.5 2121.54  1300.3 2153.95
  1360.8 2165.14  1431.4 2183.49  1451.5 2190.66  1501.9 2201.31  1532.2 2210.88
  1582.6 2221.05  1633.0 2222.91  1663.2 2227.27  1723.7 2253.22  1753.9 2272.21
#Mann= 3 , 0 , 0
       0     0.1       0   946.6   0.045       0   961.6     0.1       0
Bank Sta=   946.6,   961.6
Exp/Cntr=0.3,0.1

Type RM Length L Ch R = 1 ,30945.4,886.1,887.9,889.8
XS GIS Cut Line= 3
     2201718.465      359337.507     2201221.039      359216.456
     2199569.222      359999.297
#Sta/Elev= 30
       0 2267.68    60.2 2255.23   120.5 2252.26   200.8 2239.39   351.3 2243.32
   471.8 2231.05   582.2 2232.04   642.5 2212.21   672.6 2208.55   773.1 2160.14
   823.3 2144.65   883.6 2120.44   963.9 2111.29  1004.1 2096.87  1048.3 2096.57
  1063.3 2096.65  1205.0 2095.83  1355.6 2098.36  1506.3 2108.11  1767.4 2137.28
  1857.8 2158.87  1928.1 2181.72  1968.3 2199.08  1978.3 2207.46  2048.6 2246.52
  2068.7 2262.25  2149.0 2306.51  2189.2 2322.34  2239.4 2349.70  2339.9 2391.82
#Mann= 3 , 0 , 0
       0     0.1       0  1048.3   0.045       0  1063.3     0.1       0
Bank Sta=  1048.3,  1063.3
Exp/Cntr=0.3,0.1

Type RM Length L Ch R = 1 ,30057.4,1674,1746.7,1600
XS GIS Cut Line= 3
     2201289.877      358625.294     2200803.653      358500.622
     2199184.753      359110.607
#Sta/Elev= 30
       0 2291.99   150.6 2281.25   210.8 2272.63   391.5 2255.42   471.8 2245.15
   552.2 2226.13   703.1 2182.87   733.3 2166.29   803.7 2141.28   813.8 2135.15
   874.1 2115.65   924.4 2095.18   939.4 2091.93   954.4 2091.72   994.8 2091.56
  1276.4 2095.58  1497.7 2102.91  1558.1 2110.17  1708.9 2121.79  1809.5 2138.74
  1910.1 2151.56  1950.3 2172.53  1970.4 2189.72  2040.8 2230.28  2061.0 2245.56
  2131.4 2283.26  2141.4 2294.67  2201.8 2326.14  2221.9 2342.02  2232.0 2346.02
#Mann= 3 , 0 , 0
       0     0.1       0   939.4   0.045       0   954.4     0.1       0
Bank Sta=   939.4,   954.4
Exp/Cntr=0.3,0.1

Type RM Length L Ch R = 1 ,28309.5,1352.4,1353.4,1354.4
XS GIS Cut Line= 3
     2200842.380      357566.430     2199844.636      357475.883
     2198122.324      358227.710
#Sta/Elev= 30
       0 2228.51   160.3 2213.90   330.6 2187.95   410.8 2192.05   460.8 2181.39
   541.0 2180.35   591.1 2187.43   681.2 2181.13   851.6 2117.47   931.7 2098.11
  1072.2 2082.36  1334.5 2078.14  1349.5 2077.81  1444.0 2077.32  1574.7 2080.69
  1685.2 2106.64  1926.4 2146.40  1986.7 2162.41  2016.8 2176.36  2117.3 2239.96
  2177.6 2272.49  2227.9 2311.74  2268.1 2337.11  2438.9 2421.44  2469.1 2423.73
  2509.3 2419.38  2619.8 2385.04  2710.3 2381.47  2750.5 2383.54  2881.1 2426.58
#Mann= 3 , 0 , 0
       0     0.1       0  1334.5   0.045       0  1349.5     0.1       0
Bank Sta=  1334.5,  1349.5
Exp/Cntr=0.3,0.1

Type RM Length L Ch R = 1 ,26955.3,1107.1,1104.9,1102.6
XS GIS Cut Line= 2
     2199909.571      356211.335     2198088.072      356999.181
#Sta/Elev= 30
       0 2175.34   120.9 2163.53   191.4 2153.53   211.6 2153.20   302.2 2123.59
   312.3 2118.82   392.9 2096.69   503.7 2081.80   554.1 2071.39   695.1 2067.37
   918.5 2065.38   926.8 2065.37   933.5 2065.37  1178.7 2083.29  1279.4 2098.38
  1319.7 2107.04  1480.9 2130.97  1491.0 2135.82  1551.4 2151.90  1642.1 2189.43
  1662.2 2203.92  1692.4 2216.71  1732.7 2240.69  1742.8 2248.93  1773.0 2264.72
  1833.5 2293.70  1893.9 2319.44  1914.1 2330.62  1964.4 2352.50  1984.6 2357.83
#Mann= 3 , 0 , 0
       0     0.1       0   918.5   0.045       0   933.5     0.1       0
Bank Sta=   918.5,   933.5
Exp/Cntr=0.3,0.1

Type RM Length L Ch R = 1 ,25849.5,814.7,815,815.4
XS GIS Cut Line= 4
     2199720.488      355391.976     2198849.318      355524.989
     2198066.357      355899.809     2197582.387      356403.333
#Sta/Elev= 30
       0 2199.96    60.1 2184.58    90.1 2168.53   100.1 2159.82   190.3 2132.87
   250.4 2131.19   380.6 2120.59   560.8 2114.46   630.9 2106.17   811.2 2068.86
   962.0 2062.10  1194.2 2060.72  1224.4 2057.82  1232.5 2057.85  1247.5 2058.20
  1597.9 2074.42  1719.0 2103.96  1809.2 2120.62  1839.1 2130.49  1869.0 2144.77
  1909.0 2168.30  1948.9 2186.61  1968.8 2200.23  2068.6 2250.48  2088.5 2264.52
  2138.4 2292.53  2198.3 2322.66  2357.9 2340.28  2367.9 2339.14  2447.7 2354.76
#Mann= 3 , 0 , 0
       0     0.1       0  1232.5   0.045       0  1247.5     0.1       0
Bank Sta=  1232.5,  1247.5
Exp/Cntr=0.3,0.1

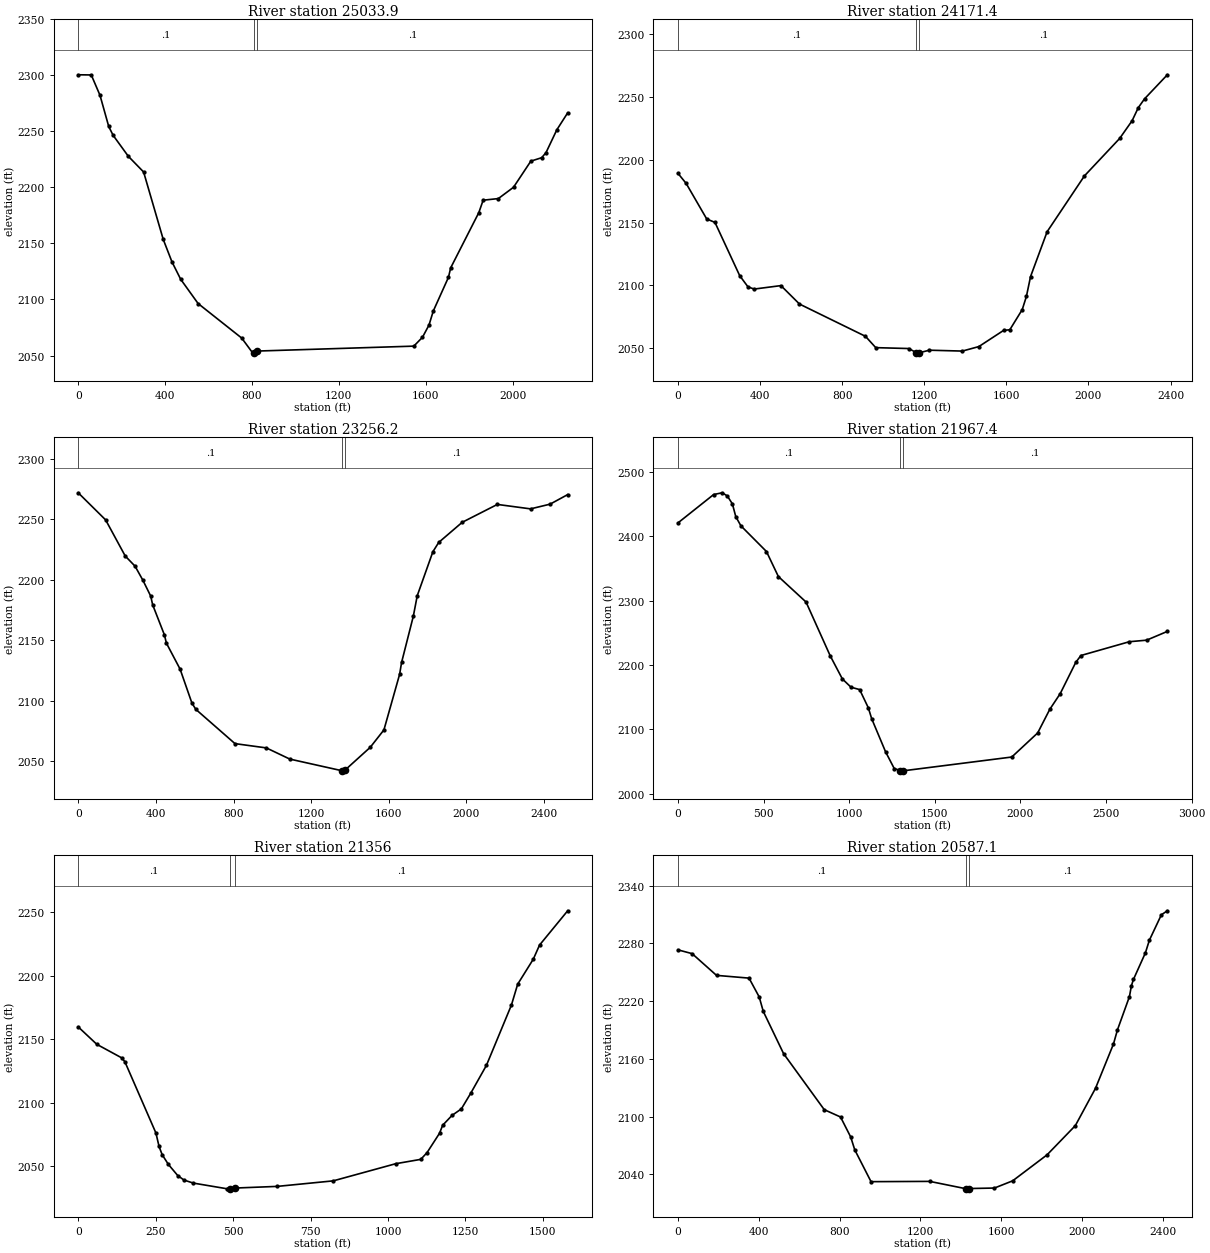
Type RM Length L Ch R = 1 ,25033.9,854.8,861.8,869.1
XS GIS Cut Line= 3
     2199121.726      354591.525     2197793.735      355161.650
     2197010.299      354963.388
#Sta/Elev= 30
       0 2300.42    60.2 2300.27   100.4 2282.08   140.5 2254.31   160.6 2246.45
   230.8 2227.69   301.1 2213.70   391.4 2153.60   431.6 2133.53   471.7 2118.03
   552.0 2096.35   752.7 2065.56   802.9 2052.38   809.5 2052.51   824.5 2053.97
  1545.0 2058.36  1584.9 2066.29  1614.8 2077.12  1634.8 2089.76  1704.6 2119.82
  1714.6 2128.15  1844.3 2177.49  1864.2 2188.54  1934.1 2189.99  2003.9 2200.06
  2083.7 2223.38  2133.6 2226.45  2153.6 2231.00  2203.4 2251.34  2253.3 2266.46
#Mann= 3 , 0 , 0
       0     0.1       0   809.5   0.045       0   824.5     0.1       0
Bank Sta=   809.5,   824.5
Exp/Cntr=0.3,0.1

Type RM Length L Ch R = 1 ,24171.4,913.3,914.4,915.3
XS GIS Cut Line= 3
     2198907.432      353936.037     2197444.533      354436.915
     2196606.922      354459.167
#Sta/Elev= 30
       0 2189.25    40.2 2181.19   140.6 2152.85   180.7 2150.14   301.2 2107.77
   341.4 2098.89   371.5 2097.11   502.0 2099.87   592.4 2085.20   913.7 2059.54
   963.9 2050.52  1124.6 2049.81  1161.7 2046.55  1164.7 2046.39  1176.7 2046.49
  1225.0 2048.49  1385.6 2047.79  1465.9 2051.36  1586.6 2064.24  1616.9 2064.75
  1677.5 2080.82  1697.7 2091.29  1717.9 2107.07  1798.6 2142.73  1980.4 2187.15
  2152.0 2216.94  2212.6 2231.02  2242.8 2241.45  2273.1 2248.42  2384.2 2267.57
#Mann= 3 , 0 , 0
       0     0.1       0  1161.7   0.045       0  1176.7     0.1       0
Bank Sta=  1161.7,  1176.7
Exp/Cntr=0.3,0.1

Type RM Length L Ch R = 1 ,23256.2,1295.2,1289.1,1282.2
XS GIS Cut Line= 3
     2198774.724      353738.946     2197020.226      353654.899
     2196264.552      353772.391
#Sta/Elev= 30
       0 2271.95   141.3 2249.50   242.3 2219.59   292.8 2211.21   333.1 2199.60
   373.5 2186.44   383.6 2179.20   444.2 2154.28   454.3 2147.52   524.9 2125.98
   585.5 2098.01   605.7 2092.73   807.6 2064.34   969.1 2060.80  1090.2 2051.54
  1361.2 2041.82  1376.2 2042.69  1504.1 2061.25  1574.8 2075.70  1655.6 2121.69
  1665.7 2131.51  1726.2 2169.76  1746.4 2186.75  1827.0 2223.17  1857.1 2230.87
  1977.9 2247.50  2159.0 2262.31  2330.1 2258.63  2430.7 2262.54  2521.3 2270.43
#Mann= 3 , 0 , 0
       0     0.1       0  1361.2   0.045       0  1376.2     0.1       0
Bank Sta=  1361.2,  1376.2
Exp/Cntr=0.3,0.1

Type RM Length L Ch R = 1 ,21967.4,620.9,611.4,602.6
XS GIS Cut Line= 3
     2199051.056      352435.878     2198464.755      352410.661
     2196279.179      353028.439
#Sta/Elev= 30
       0 2420.48   208.9 2464.64   258.6 2467.37   288.4 2462.54   318.3 2450.17
   338.2 2430.28   368.0 2416.08   517.2 2376.20   586.8 2337.33   748.4 2297.75
   889.7 2214.16   960.3 2178.40  1010.8 2165.52  1061.3 2161.82  1111.7 2133.73
  1131.9 2116.45  1212.7 2065.26  1263.2 2039.29  1299.7 2036.02  1313.6 2035.67
  1314.7 2035.68  1949.6 2057.11  2101.0 2094.56  2171.6 2131.19  2232.2 2155.39
  2323.1 2203.98  2353.3 2214.72  2636.0 2236.13  2736.9 2238.53  2858.0 2252.15
#Mann= 3 , 0 , 0
       0     0.1       0  1299.7   0.045       0  1314.7     0.1       0
Bank Sta=  1299.7,  1314.7
Exp/Cntr=0.3,0.1

Type RM Length L Ch R = 1 ,21356,760,768.7,777.5
XS GIS Cut Line= 3
     2197898.100      351746.017     2197293.762      352243.707
     2196511.679      352397.753
#Sta/Elev= 30
       0 2159.72    60.2 2145.99   140.5 2135.35   150.6 2132.35   250.9 2076.26
   261.0 2065.69   271.0 2059.26   291.1 2051.58   321.2 2042.85   341.3 2039.30
   371.4 2036.91   481.8 2032.38   491.3 2032.41   506.3 2033.00   642.4 2034.30
   823.2 2038.65  1025.0 2052.14  1105.8 2055.56  1126.0 2060.85  1166.3 2076.06
  1176.4 2082.35  1206.7 2090.13  1236.9 2095.26  1267.2 2107.60  1317.7 2129.46
  1398.4 2176.87  1418.6 2193.29  1469.0 2212.95  1489.2 2224.05  1580.0 2251.01
#Mann= 3 , 0 , 0
       0     0.1       0   491.3   0.045       0   506.3     0.1       0
Bank Sta=   491.3,   506.3
Exp/Cntr=0.3,0.1

Type RM Length L Ch R = 1 ,20587.1,1133.8,1141.4,1148.8
XS GIS Cut Line= 4
     2198515.190      351483.928     2197556.935      351301.103
     2196548.246      351628.927     2196184.637      351755.281
#Sta/Elev= 30
       0 2273.31    70.4 2269.35   191.1 2246.78   352.0 2243.93   402.3 2224.38
   422.4 2209.38   523.0 2165.46   724.1 2107.30   804.6 2099.70   854.8 2078.96
   875.0 2065.59   955.4 2032.55  1245.7 2032.84  1423.3 2025.28  1425.8 2025.10
  1438.3 2025.40  1565.9 2025.93  1655.9 2033.41  1826.0 2060.38  1966.1 2090.79
  2065.8 2129.53  2154.6 2175.49  2174.4 2190.25  2233.6 2224.74  2243.4 2236.07
  2253.3 2242.51  2312.5 2270.14  2332.3 2283.35  2391.5 2309.68  2421.1 2313.86
#Mann= 3 , 0 , 0
       0     0.1       0  1423.3   0.045       0  1438.3     0.1       0
Bank Sta=  1423.3,  1438.3
Exp/Cntr=0.3,0.1