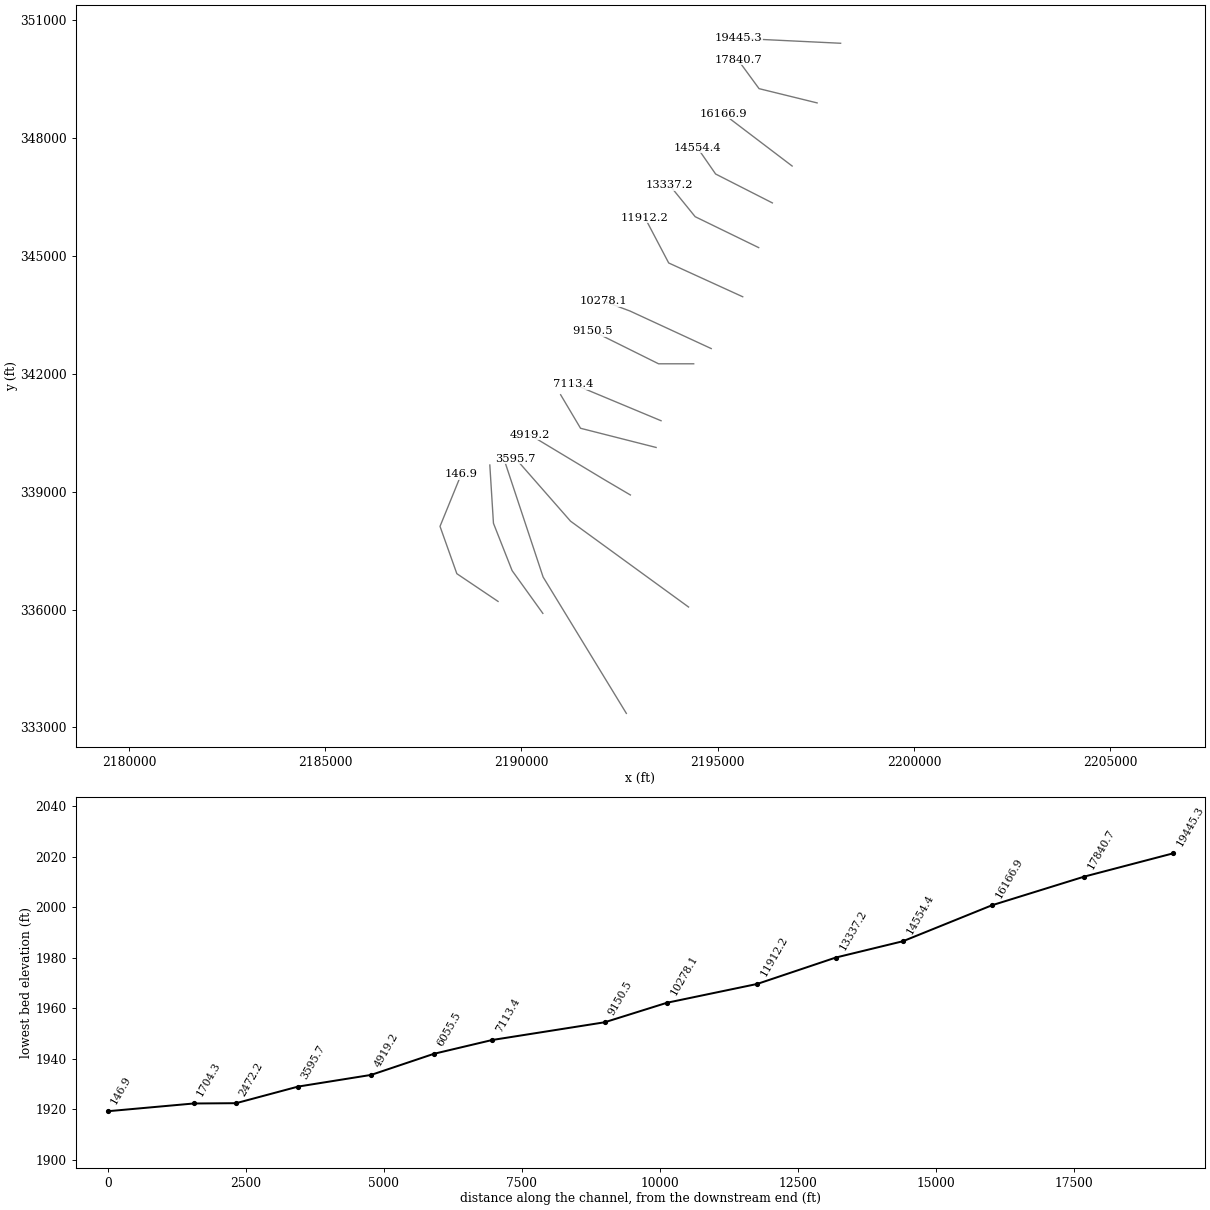
HEC-RAS study LittleCk.prj: LittleCk

--- LittleCk.g01 (geometry) --- (continued)

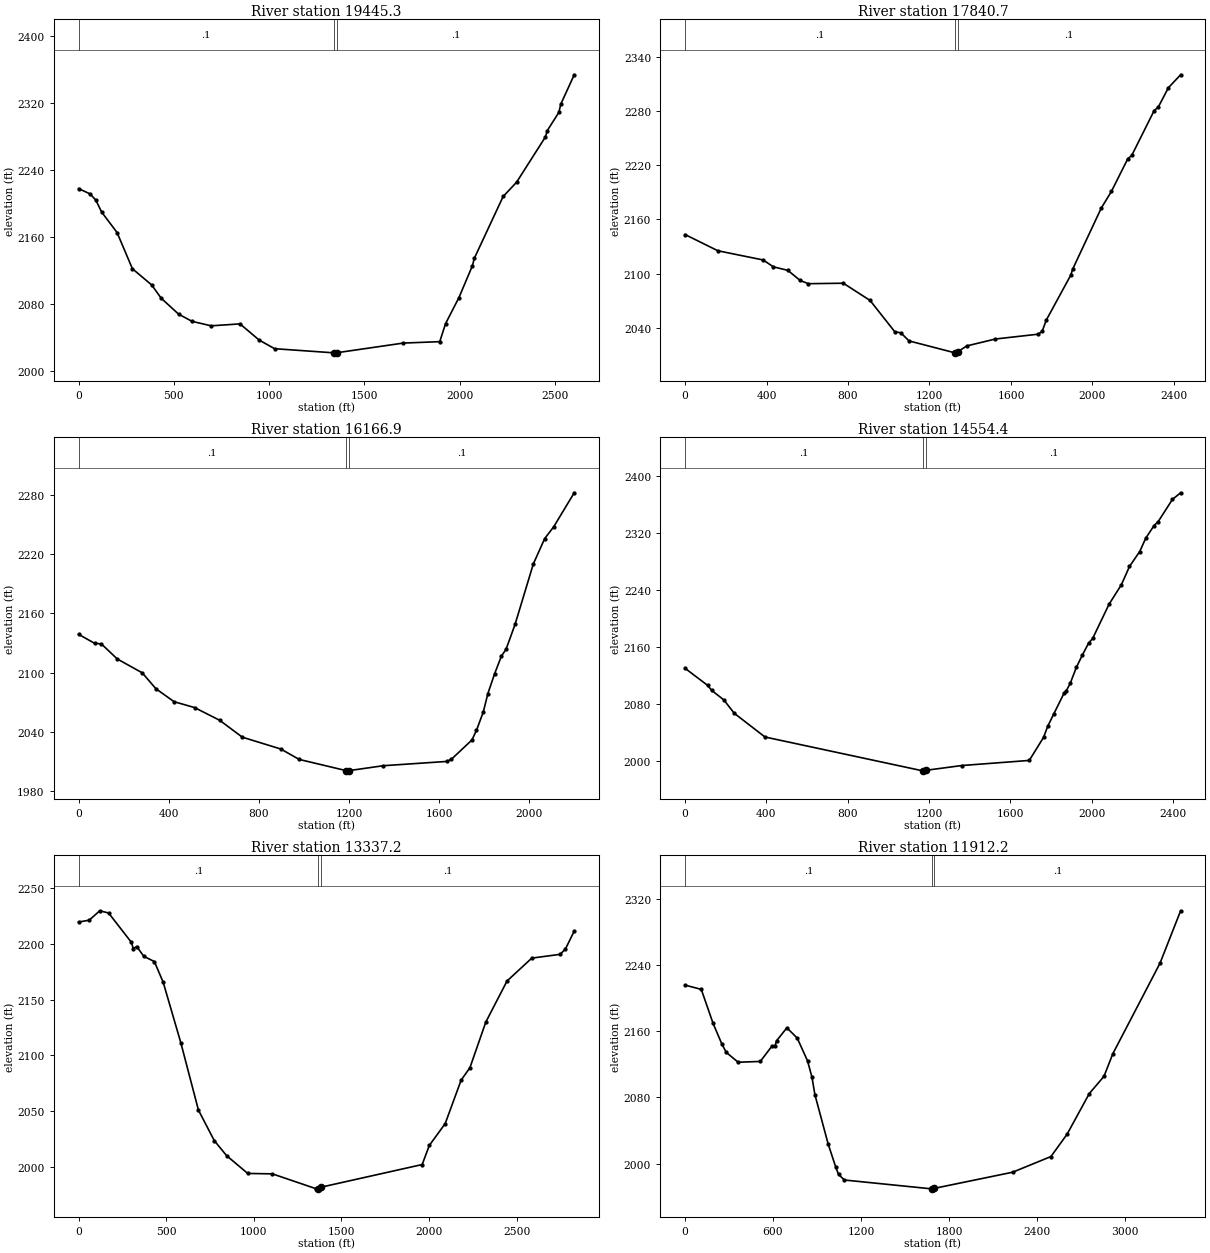
Type RM Length L Ch R = 1 ,19445.3,1607.5,1604.4,1601.2
XS GIS Cut Line= 2
     2198132.191      350419.095     2195533.252      350544.586
#Sta/Elev= 30
       0 2217.75    60.5 2211.42    90.8 2203.79   121.0 2189.65   201.7 2165.30
   282.4 2121.93   383.2 2102.65   433.7 2086.63   524.4 2067.75   595.0 2059.08
   695.9 2053.70   847.2 2056.01   948.0 2036.63  1028.7 2026.35  1339.1 2021.41
  1341.3 2021.39  1354.1 2021.47  1704.4 2033.07  1896.0 2034.77  1926.3 2056.24
  1996.9 2087.56  2067.4 2125.57  2077.5 2134.48  2228.8 2208.38  2299.4 2225.44
  2450.7 2279.57  2460.8 2287.22  2521.3 2308.96  2531.4 2318.78  2602.0 2353.92
#Mann= 3 , 0 , 0
       0     0.1       0  1339.1   0.045       0  1354.1     0.1       0
Bank Sta=  1339.1,  1354.1
Exp/Cntr=0.3,0.1

Type RM Length L Ch R = 1 ,17840.7,1680.7,1673,1665.3
XS GIS Cut Line= 3
     2197533.429      348900.128     2196053.676      349263.401
     2195516.544      349996.809
#Sta/Elev= 30
       0 2143.31   161.4 2125.30   383.4 2115.12   433.9 2107.49   504.5 2103.62
   565.1 2092.42   605.4 2088.82   777.0 2089.34   908.2 2070.28  1029.2 2035.68
  1059.5 2034.30  1099.9 2025.39  1322.8 2012.33  1332.0 2012.20  1337.8 2013.18
  1382.4 2019.84  1523.7 2027.53  1733.5 2032.87  1753.4 2036.22  1773.4 2048.52
  1893.3 2098.23  1903.3 2105.18  2043.2 2172.60  2093.1 2191.11  2173.0 2227.09
  2193.0 2231.03  2302.9 2280.68  2322.9 2284.45  2372.8 2306.03  2432.8 2320.33
#Mann= 3 , 0 , 0
       0     0.1       0  1322.8   0.045       0  1337.8     0.1       0
Bank Sta=  1322.8,  1337.8
Exp/Cntr=0.3,0.1

Type RM Length L Ch R = 1 ,16166.9,1607.2,1611.7,1616
XS GIS Cut Line= 2
     2196896.850      347292.923     2195144.681      348622.807
#Sta/Elev= 30
       0 2138.85    70.6 2129.81   100.9 2129.17   171.5 2113.96   282.5 2099.90
   343.1 2083.82   423.8 2070.74   514.6 2064.81   625.6 2052.01   726.5 2034.88
   898.0 2022.85   978.8 2012.38    1186 2001.13  1190.7 2000.84    1201 2001.09
  1352.1 2006.02  1634.6 2010.35  1654.8 2012.62  1745.6 2032.02  1765.8 2041.77
  1796.1 2060.40  1816.3 2078.90  1846.5 2099.13  1876.8 2116.98  1897.0 2123.66
  1937.4 2149.13  2018.1 2210.00  2068.5 2235.64  2108.9 2247.70  2199.7 2281.98
#Mann= 3 , 0 , 0
       0     0.1       0    1186   0.045       0    1201     0.1       0
Bank Sta=    1186,    1201
Exp/Cntr=0.3,0.1

Type RM Length L Ch R = 1 ,14554.4,1217,1216.9,1216.2
XS GIS Cut Line= 3
     2196392.628      346353.811     2194946.952      347089.825
     2194482.891      347759.328
#Sta/Elev= 30
       0 2130.32   110.8 2106.43   131.0 2099.36   191.4 2085.83   241.8 2067.31
   393.0 2034.02  1168.8 1986.59  1172.1 1986.66  1187.1 1987.44  1360.3 1994.01
  1692.6 2001.18  1763.0 2033.51  1783.2 2048.97  1813.3 2066.43  1863.6 2095.44
  1873.7 2098.25  1893.8 2109.04  1924.0 2131.48  1954.1 2149.07  1984.3 2165.54
  2004.4 2172.13  2084.9 2220.10  2145.2 2247.21  2185.4 2272.97  2235.7 2293.96
  2265.9 2312.91  2306.1 2330.30  2326.2 2335.75  2396.6 2366.99  2436.9 2376.28
#Mann= 3 , 0 , 0
       0     0.1       0  1172.1   0.045       0  1187.1     0.1       0
Bank Sta=  1172.1,  1187.1
Exp/Cntr=0.3,0.1

Type RM Length L Ch R = 1 ,13337.2,1424,1424.8,1425.6
XS GIS Cut Line= 3
     2196044.034      345215.565     2194425.914      346002.626
     2193776.981      346801.308
#Sta/Elev= 30
       0 2219.82    60.3 2221.47   120.6 2229.92   170.9 2227.94   301.6 2201.48
   311.6 2195.92   331.7 2197.80   371.9 2188.99   432.2 2184.32   482.5 2165.74
   583.0 2111.49   683.6 2050.92   774.0 2023.47   844.4 2009.94   965.0 1993.96
  1105.8 1993.57  1357.1 1980.12  1368.1 1980.25  1383.1 1981.59  1960.8 2001.95
  2001.2 2019.07  2092.0 2038.72  2182.8 2077.70  2233.2 2088.95  2324.0 2130.00
  2445.1 2166.85  2586.3 2187.40  2747.8 2190.78  2778.0 2195.52  2828.5 2211.64
#Mann= 3 , 0 , 0
       0     0.1       0  1368.1   0.045       0  1383.1     0.1       0
Bank Sta=  1368.1,  1383.1
Exp/Cntr=0.3,0.1

Type RM Length L Ch R = 1 ,11912.2,1599.9,1633.9,1651.6
XS GIS Cut Line= 3
     2195637.506      343964.029     2193751.290      344824.479
     2193143.125      345980.909
#Sta/Elev= 30
       0 2215.59   110.7 2210.43   191.2 2169.41   251.6 2144.26   281.8 2134.26
   362.3 2122.49   513.3 2123.44   593.8 2142.20   613.9 2142.26   624.0 2148.34
   694.4 2164.03   764.9 2151.69   835.3 2124.18   865.5 2104.52   885.6 2083.40
   976.2 2023.65  1026.5 1996.60  1046.7 1986.99  1086.9 1980.30  1680.7 1969.65
  1685.1 1969.71  1700.1 1970.24  2234.0 1989.71  2495.3 2008.63  2605.9 2035.71
  2756.7 2084.62  2857.2 2105.49  2917.5 2132.78  3239.1 2242.00  3379.8 2305.31
#Mann= 3 , 0 , 0
       0     0.1       0  1685.1   0.045       0  1700.1     0.1       0
Bank Sta=  1685.1,  1700.1
Exp/Cntr=0.3,0.1

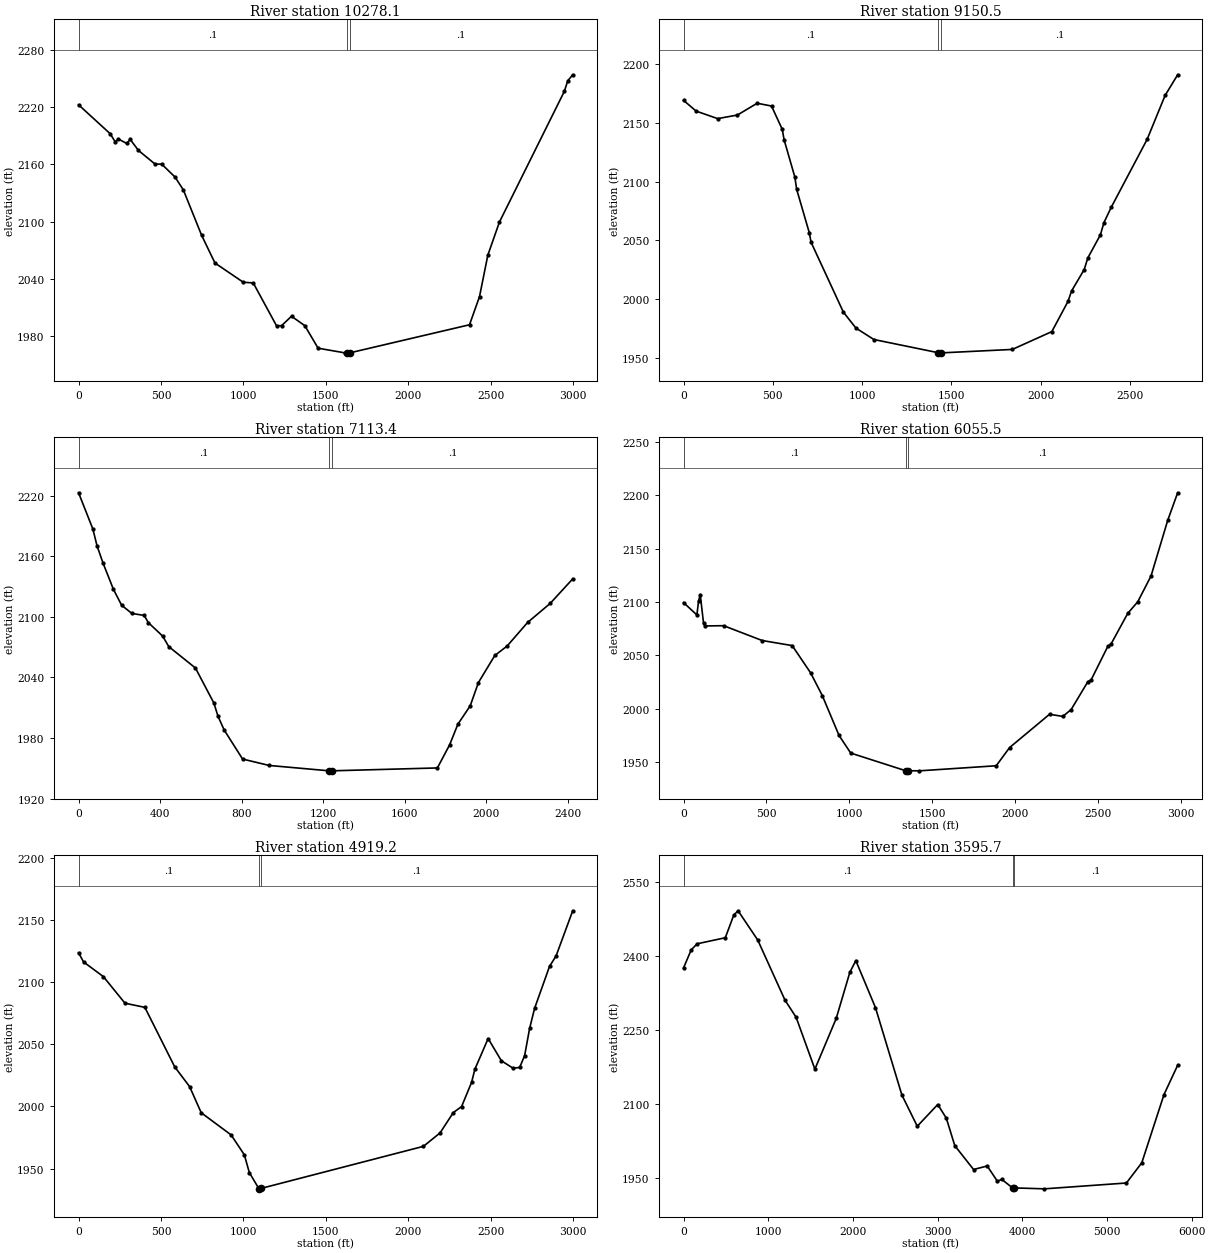
Type RM Length L Ch R = 1 ,10278.1,1160.5,1127.6,1113.9
XS GIS Cut Line= 3
     2194834.983      342644.636     2192765.306      343600.680
     2192094.143      343851.614
#Sta/Elev= 30
       0 2222.57   191.7 2192.22   221.9 2183.74   242.1 2186.59   292.5 2181.97
   312.7 2186.34   363.2 2174.67   464.0 2160.32   504.4 2160.26   585.1 2146.71
   635.5 2133.20   746.5 2085.46   827.2 2056.47   998.7 2036.31  1059.2 2035.58
  1200.4 1990.62  1230.7 1990.68  1291.2 2000.59  1371.9 1990.72  1452.6 1967.06
  1614.0 1962.20  1630.2 1962.20  1645.2 1962.21  2370.6 1991.67  2431.2 2021.22
  2481.7 2064.74  2552.3 2099.61  2945.9 2236.78  2966.1 2247.75  2996.4 2254.09
#Mann= 3 , 0 , 0
       0     0.1       0  1630.2   0.045       0  1645.2     0.1       0
Bank Sta=  1630.2,  1645.2
Exp/Cntr=0.3,0.1

Type RM Length L Ch R = 1 ,9150.5,2047.6,2038.1,2025.1
XS GIS Cut Line= 3
     2194388.349      342257.014     2193493.357      342257.014
     2191816.821      343088.979
#Sta/Elev= 30
       0 2169.11    70.4 2159.95   191.1 2153.54   301.7 2156.58   412.3 2166.60
   492.8 2164.24   553.1 2144.35   563.1 2135.61   623.5 2103.80   633.5 2093.47
   703.9 2056.74   714.0 2048.54   895.0 1989.09   965.4 1975.51  1066.0 1965.80
  1427.6 1954.53  1442.6 1954.48  1448.4 1954.47  1840.9 1957.37  2062.2 1972.52
  2152.8 1998.24  2172.9 2007.13  2243.4 2025.27  2263.5 2035.10  2333.9 2054.72
  2354.0 2065.19  2394.3 2078.07  2595.5 2135.85  2696.2 2173.23  2766.6 2190.80
#Mann= 3 , 0 , 0
       0     0.1       0  1427.6   0.045       0  1442.6     0.1       0
Bank Sta=  1427.6,  1442.6
Exp/Cntr=0.3,0.1

Type RM Length L Ch R = 1 ,7113.4,1040.2,1055.7,1068
XS GIS Cut Line= 2
     2193556.384      340807.378     2191318.903      341740.187
#Sta/Elev= 30
       0 2223.07    70.4 2187.03    90.5 2170.53   120.7 2153.04   171.0 2127.38
   211.2 2111.60   261.5 2103.47   321.9 2101.49   342.0 2094.43   412.4 2081.02
   442.6 2070.57   573.3 2049.39   663.9 2014.60   684.0 2001.56   714.2 1987.95
   804.7 1959.11   935.5 1952.76    1228 1947.48  1237.2 1947.44    1243 1947.46
  1760.3 1950.32  1820.6 1973.36  1860.8 1993.70  1921.2 2011.84  1961.4 2034.90
  2041.9 2061.78  2102.3 2071.15  2202.8 2094.52  2313.5 2113.38  2424.1 2137.72
#Mann= 3 , 0 , 0
       0     0.1       0    1228   0.045       0    1243     0.1       0
Bank Sta=    1228,    1243
Exp/Cntr=0.3,0.1

Type RM Length L Ch R = 1 ,6055.5,1142.4,1136.6,1130.5
XS GIS Cut Line= 3
     2193430.329      340126.680     2191504.800      340615.302
     2190997.462      341469.169
#Sta/Elev= 30
       0 2099.55    80.7 2087.94    90.8 2101.00   100.8 2107.06   121.0 2079.97
   131.1 2077.65   242.0 2077.88   474.0 2064.01   655.5 2059.25   766.4 2033.73
   837.0 2012.40   937.8 1975.15  1008.4 1958.60  1339.9 1942.07  1354.9 1942.07
  1421.8 1941.97  1885.7 1946.73  1966.4 1963.77  2207.3 1994.94  2287.5 1992.93
  2337.7 1999.40  2438.0 2025.38  2458.1 2027.16  2558.4 2058.45  2578.5 2060.84
  2678.8 2089.39  2739.0 2100.24  2819.3 2124.45  2919.6 2176.42  2979.8 2202.34
#Mann= 3 , 0 , 0
       0     0.1       0  1339.9   0.045       0  1354.9     0.1       0
Bank Sta=  1339.9,  1354.9
Exp/Cntr=0.3,0.1

Type RM Length L Ch R = 1 ,4919.2,1330.6,1323.3,1316
XS GIS Cut Line= 3
     2192774.841      338916.549     2192116.318      339304.006
     2190202.757      340455.218
#Sta/Elev= 30
       0 2123.92    30.2 2116.54   150.8 2104.67   281.5 2083.27   402.1 2079.92
   583.1 2031.97   673.6 2016.01   744.0 1994.95   925.0 1977.11  1005.5 1961.04
  1035.6 1946.77  1093.9 1933.71  1096.0 1933.61  1108.9 1934.02  2091.9 1967.88
  2192.5 1978.69  2272.9 1995.07  2323.2 1999.95  2383.6 2019.39  2403.7 2030.03
  2484.2 2054.78  2564.7 2036.83  2635.1 2030.90  2675.3 2031.44  2705.5 2041.00
  2735.7 2062.89  2765.8 2079.06  2856.4 2112.89  2896.6 2121.49  2997.2 2157.79
#Mann= 3 , 0 , 0
       0     0.1       0  1093.9   0.045       0  1108.9     0.1       0
Bank Sta=  1093.9,  1108.9
Exp/Cntr=0.3,0.1

Type RM Length L Ch R = 1 ,3595.7,1131.6,1123.5,1115.3
XS GIS Cut Line= 3
     2194257.077      336063.511     2191250.391      338249.154
     2189853.734      339841.115
#Sta/Elev= 30
       0 2375.44    90.7 2412.07   161.2 2424.42   493.6 2436.67   594.3 2482.78
   644.7 2491.16   876.4 2432.06  1198.8 2310.31  1329.7 2275.87  1551.3 2170.96
  1803.2 2273.48  1964.4 2366.86  2034.9 2390.42  2266.6 2295.37  2578.8 2118.62
  2760.2 2055.54  3001.9 2099.44  3102.7 2072.10  3203.4 2016.26  3425.0 1968.05
  3586.2 1975.22  3707.1 1944.15  3757.5 1948.23  3889.8 1930.22  3904.8 1930.87
  4261.7 1928.98  5229.8 1940.78  5411.4 1981.67  5673.6 2119.60  5834.9 2178.82
#Mann= 3 , 0 , 0
       0     0.1       0  3889.8   0.045       0  3904.8     0.1       0
Bank Sta=  3889.8,  3904.8
Exp/Cntr=0.3,0.1

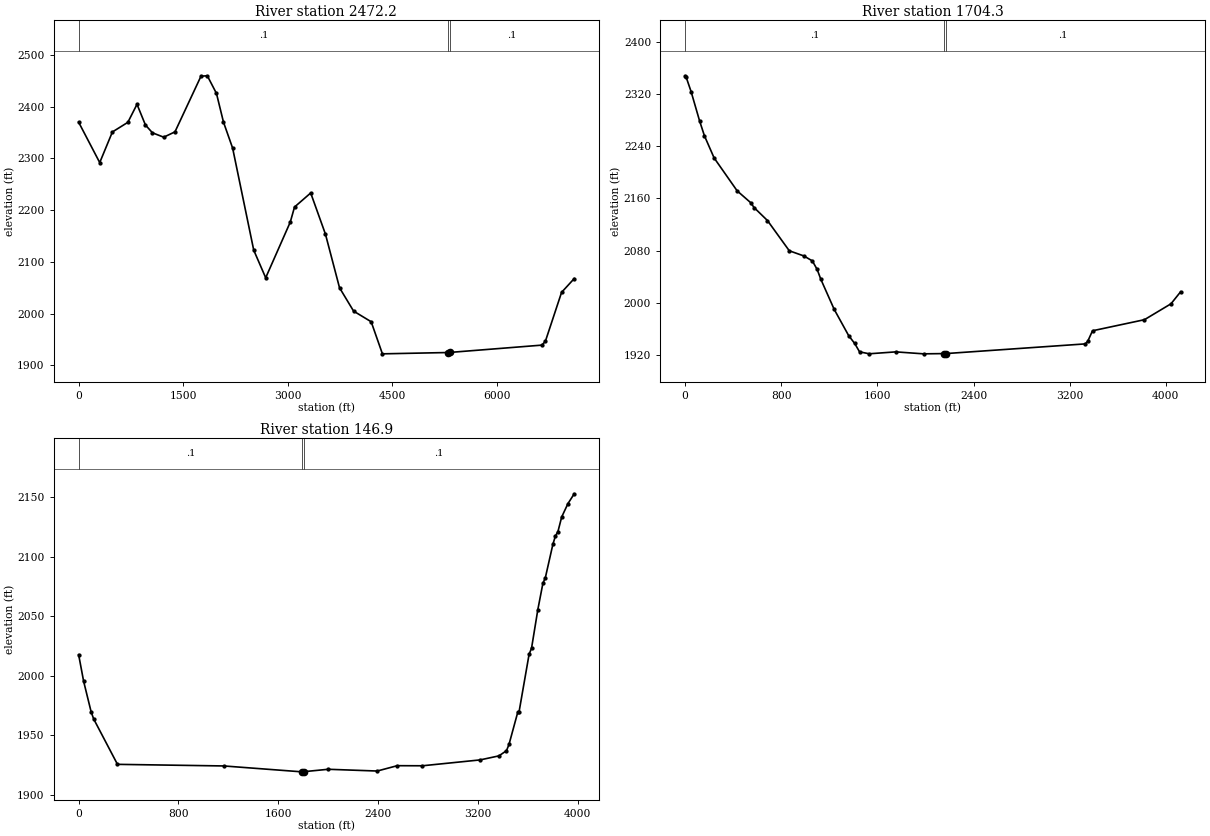
Type RM Length L Ch R = 1 ,2472.2,766.7,767.7,768.7
XS GIS Cut Line= 3
     2192672.361      333355.208     2190551.256      336827.184
     2189591.426      339718.523
#Sta/Elev= 30
       0 2369.96   302.9 2291.90   484.6 2351.09   706.7 2369.73   838.0 2404.53
   959.1 2364.54  1060.1 2349.43  1221.6 2341.00  1383.1 2351.30  1756.7 2458.91
  1847.5 2459.65  1978.8 2425.52  2079.7 2370.00  2211.0 2319.82  2513.9 2122.68
  2685.5 2069.35  3038.8 2177.11  3099.4 2206.05  3331.6 2233.21  3543.6 2153.57
  3745.6 2050.04  3947.5 2004.96  4199.8 1984.42  4361.2 1922.40  5309.6 1924.96
  5324.6 1925.08  6651.1 1939.24  6701.5 1946.87  6933.5 2041.20  7115.1 2067.85
#Mann= 3 , 0 , 0
       0     0.1       0  5309.6   0.045       0  5324.6     0.1       0
Bank Sta=  5309.6,  5324.6
Exp/Cntr=0.3,0.1

Type RM Length L Ch R = 1 ,1704.3,1556.1,1557.1,1557.2
XS GIS Cut Line= 4
     2190544.426      335901.747     2189761.032      336990.531
     2189285.935      338195.656     2189193.233      339678.887
#Sta/Elev= 30
       0 2347.73    10.1 2345.22    50.4 2323.51   121.0 2278.70   161.4 2255.86
   242.0 2221.98   433.7 2171.63   544.6 2153.81   574.8 2146.03   685.8 2126.22
   867.3 2079.97   988.4 2072.07  1058.9 2064.50  1099.3 2051.33  1129.5 2036.43
  1240.5 1990.44  1361.4 1950.09  1411.6 1938.10  1451.8 1925.34  1532.1 1922.37
  1753.0 1925.29  1984.0 1922.28  2151.8 1922.66  2166.8 1922.65  3329.6 1937.50
  3349.7 1941.41  3389.8 1957.57  3821.6 1974.51  4042.5 1998.85  4122.8 2017.26
#Mann= 3 , 0 , 0
       0     0.1       0  2151.8   0.045       0  2166.8     0.1       0
Bank Sta=  2151.8,  2166.8
Exp/Cntr=0.3,0.1

Type RM Length L Ch R = 1 ,146.9,144.5,146.9,149.3
XS GIS Cut Line= 4
     2189402.862      336206.360     2188352.897      336912.162
     2187924.151      338117.287     2188463.750      339439.678
#Sta/Elev= 30
       0 2017.62    40.2 1995.18   100.4 1969.49   120.5 1963.62   311.3 1925.50
  1164.7 1924.15  1788.9 1919.21  1793.5 1919.23  1808.5 1919.38  2000.4 1921.36
  2393.2 1919.89  2554.3 1924.38  2755.5 1924.30  3218.2 1929.23  3369.0 1932.62
  3429.4 1936.97  3449.5 1942.18  3519.9 1969.29  3530.0 1969.44  3610.4 2017.76
  3630.5 2023.14  3680.8 2055.49  3721.1 2077.40  3741.2 2082.35  3801.5 2110.33
  3821.6 2117.23  3841.8 2120.95  3871.9 2133.23  3922.2 2144.48  3972.5 2152.73
#Mann= 3 , 0 , 0
       0     0.1       0  1793.5   0.045       0  1808.5     0.1       0
Bank Sta=  1793.5,  1808.5
Exp/Cntr=0.3,0.1